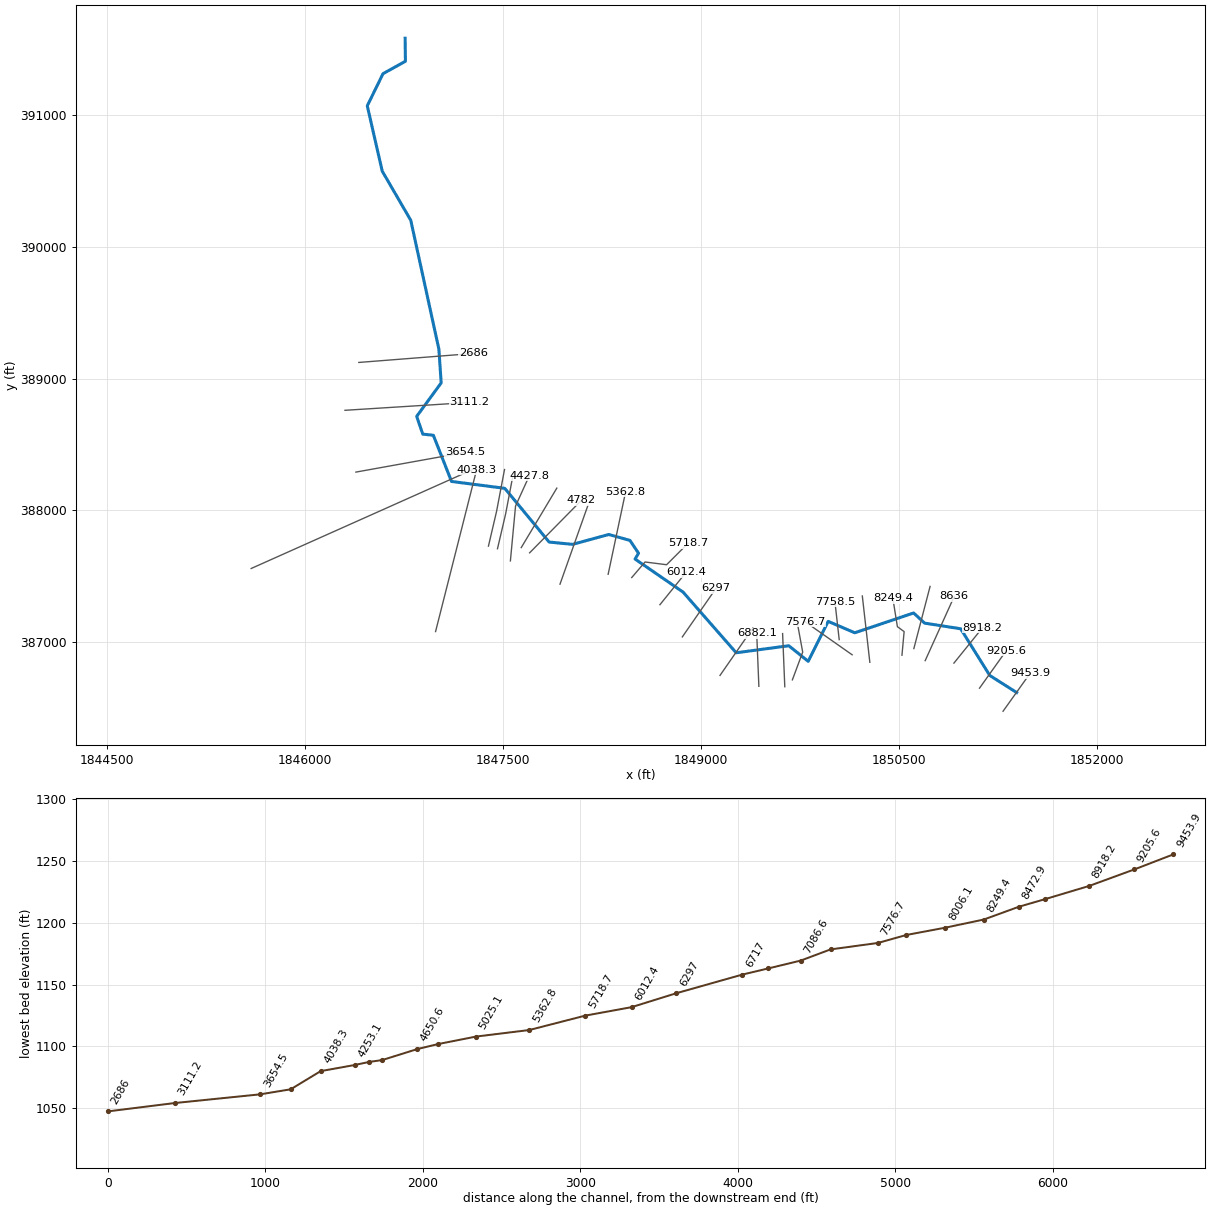
--- MountnRun.prj (project) ---

Proj Title=MountnRun
Current Plan=p01
Default Exp/Contr=0,0
English Units
Geom File=g01
Flow File=f01
Plan File=p01
BEGIN DESCRIPTION:
END DESCRIPTION:
DSS Export Rating Curves= 0
DSS Export Rating Curve Sorted= 0
DSS Export Volume Flow Curves= 0
DXF Filename=C:\temp\junk\MountnRun.
DXF OffsetX= 0
DXF OffsetY= 0
DXF ScaleX= 0
DXF ScaleY= 0

--- MountnRun.p01 (plan) ---

Plan Title=Floodplain
Program Version=4.00
Geom File=g01
Flow File=f01
K Sum by GR=0
Std Step Tol=0.01
Critical Tol=0.01
Num of Std Step Trials=20
Max Error Tol=0.3
Flow Tol Ratio=0.001
Split Flow NTrial=30
Split Flow Tol=0.02
Split Flow Ratio=0.02
Log Output Level=0
Friction Slope Method=1
Unsteady Friction Slope Method=2
Unsteady Bridges Friction Slope Method=1
Global Log Level=0
CheckData=False
Run HTab=0
Run UNet=0
Run PostProcess=0
UNET Theta=0
UNET Theta Warmup=0
UNET ZTol=0
UNET ZSATol=0
UNET MxIter=0
UNET MaxInSteps=0
UNET DtIC=0
UNET DtMin=0
UNET MaxCRTS=0
UNET WFStab=0
UNET SFStab=0
UNET WFX=0
UNET SFX=0
UNET DSS MLevel=0
UNET DZMax Abort=0
UNET Convert EG Bridges=0
UNET Use Existing IB Tables=0
UNET Froude Limit=0
UNET Froude Power=0
Write IC File=0
Echo Input=False
Echo Output=False
Write Detailed=0

--- MountnRun.f01 (steady flow) ---

Flow Title=NFF Regression Equation
Program Version=4.00
Number of Profiles=1
Profile Names=P100yr
River Rch & RM=MountnRun,Main      ,9453.9
     885
River Rch & RM=MountnRun,Main      ,6882.1
     969
River Rch & RM=MountnRun,Main      ,5362.8
    1072
River Rch & RM=MountnRun,Main      ,2686
    1111
Boundary for River Rch & Prof#=MountnRun,Main      ,1
Up Type=0
Dn Type=3
Dn Slope=0.022038

--- MountnRun.g01 (geometry) ---

Geom Title=USGS 10m DEM
Program Version=4.10

River Reach=MountnRun       ,Main
Reach XY= 30
     1851388.633      386618.046     1851184.654       386747.77
      1850964.66      387101.871     1850691.346      387144.814
     1850608.144      387221.753     1850162.431      387071.453
     1849960.956      387158.234     1849809.761      386854.948
     1849662.491      386973.205     1849264.291      386919.811
     1848862.055      387380.186     1848498.474      387630.975
     1848524.793      387675.356      1848459.77      387772.374
      1848299.69      387817.271     1848024.788      387742.443
     1847847.575      387759.886     1847511.727      388167.466
     1847108.482      388219.587     1846970.799      388569.885
     1846890.602      388578.881     1846844.521      388713.389
     1847030.091      388967.458     1847012.655       389223.52
     1846799.686      390201.188     1846583.602      390574.072
     1846470.267      391069.507     1846589.829      391313.613
     1846759.209      391407.519     1846757.087      391582.365

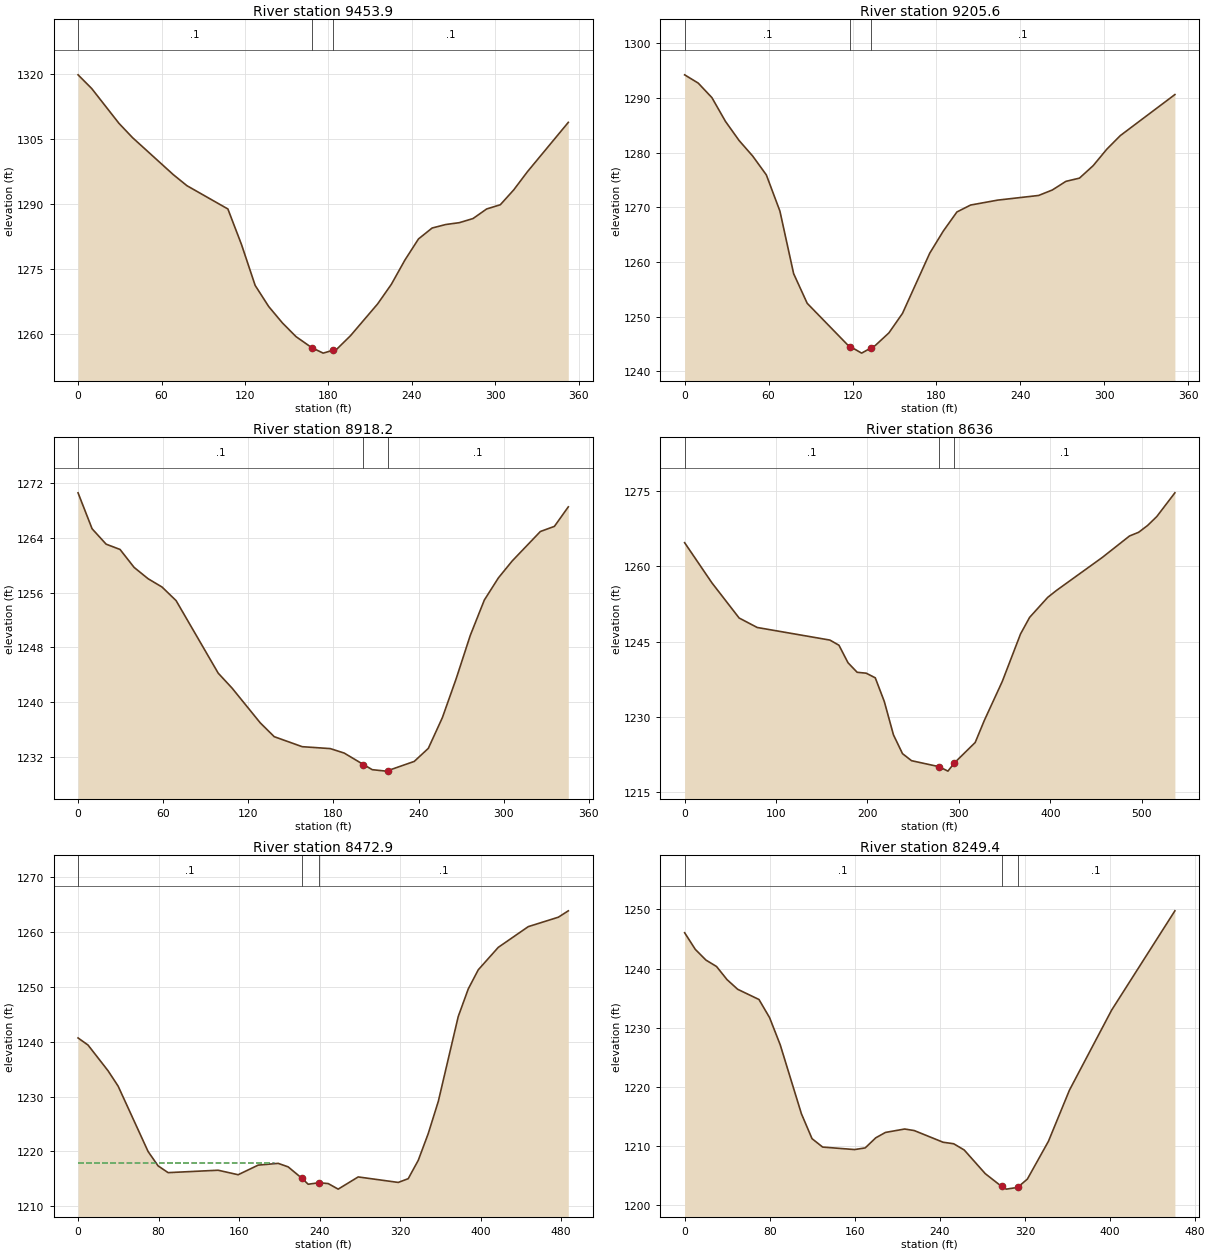
Type RM Length L Ch R = 1 ,9453.9  ,248.1,248.3,248.5
XS GIS Cut Line= 2
     1851285.408      386476.151     1851489.868      386763.175
#Sta/Elev= 30
       0 1319.82     9.8 1316.66    29.4 1308.62    39.2  1305.3    68.5 1296.76
    78.3 1294.21   107.7 1288.84   117.5 1280.62   127.3 1271.19     137 1266.33
   146.8 1262.56   156.6 1259.38     168 1256.81   176.2 1255.55     183 1256.19
     186 1256.47   195.8 1259.56   215.4 1266.94   225.2 1271.44   234.9 1277.02
   244.7 1281.92   254.5 1284.44   264.3 1285.25   274.1 1285.68   283.9 1286.63
   293.7 1288.84   303.5 1289.81   313.2 1293.26     323 1297.44   352.4 1308.84
#Mann= 3 , 0 , 0
       0      .1       0     168    .045       0     183      .1       0
Bank Sta=168,183
XS Rating Curve= 0 ,0
Exp/Cntr=0.3,0.1

Type RM Length L Ch R = 1 ,9205.6  ,287.6,287.3,287
XS GIS Cut Line= 2
     1851107.127      386651.304     1851310.399      386936.661
#Sta/Elev= 30
       0 1294.23     9.7 1292.72    19.5 1290.06    29.2 1285.71    38.9 1282.23
    48.7 1279.36    58.4 1275.93    68.1 1269.31    77.9 1257.88    87.6 1252.45
   116.8 1244.77   118.4 1244.53   126.5 1243.34   133.4 1244.32   136.2 1244.72
     146 1247.04   155.7  1250.6   175.2 1261.62   184.9 1265.67   194.6 1269.15
   204.4 1270.42   223.8 1271.32     253 1272.17   262.8 1273.17   272.5 1274.75
   282.2 1275.34     292 1277.62   301.7 1280.62   311.4 1283.12   350.4 1290.62
#Mann= 3 , 0 , 0
       0      .1       0   118.4    .045       0   133.4      .1       0
Bank Sta=118.4,133.4
XS Rating Curve= 0 ,0
Exp/Cntr=0.3,0.1

Type RM Length L Ch R = 1 ,8918.2  ,277.8,282.3,286.6
XS GIS Cut Line= 2
     1850913.486      386841.547     1851130.448      387110.614
#Sta/Elev= 30
       0 1270.59     9.9 1265.34    19.8 1263.09    29.6 1262.32    39.5  1259.7
    49.4 1258.04    59.2 1256.83    69.1 1254.85    98.8 1244.25   108.6 1242.06
   128.4    1237   138.3 1234.97     158 1233.51   177.8 1233.23   187.6 1232.58
   201.21230.901   207.4 1230.15   217.2 1229.94   218.21229.998     237 1231.36
   246.9 1233.26   256.8 1237.74   266.6 1243.47   276.5 1249.77   286.4 1254.93
   296.3 1258.16   306.1 1260.65   325.9 1264.94   335.8 1265.69   345.6 1268.54
#Mann= 3 , 0 , 0
       0      .1       0   201.2    .045       0   218.2      .1       0
Bank Sta=201.2,218.2
XS Rating Curve= 0 ,0
Exp/Cntr=0.3,0.1

Type RM Length L Ch R = 1 ,8636    ,155.4,163,169.8
XS GIS Cut Line= 2
     1850695.681      386860.046     1850916.286      387348.771
#Sta/Elev= 30
       0  1264.7    29.8 1256.71    59.6 1249.69    79.4  1247.8   158.9 1245.29
   168.8 1244.26   178.7 1240.77   188.7 1238.87   198.6 1238.69   208.5 1237.77
   218.4 1233.04   228.4  1226.4   238.3 1222.65   248.2 1221.25   278.11220.061
     288 1219.17   295.11220.822   317.8 1224.88   327.7 1229.24   347.5 1237.08
   367.4 1246.52   377.3 1249.81   397.2 1253.82   407.1 1255.24   456.8 1261.76
   486.6 1266.04   496.5 1266.77   506.4 1268.14   516.4 1269.91   536.2 1274.64
#Mann= 3 , 0 , 0
       0      .1       0   278.1    .045       0   295.1      .1       0
Bank Sta=278.1,295.1
XS Rating Curve= 0 ,0
Exp/Cntr=0.3,0.1

Type RM Length L Ch R = 1 ,8472.9  ,215.8,223.6,231.5
XS GIS Cut Line= 2
     1850609.932      386951.736     1850732.771      387423.205
#Sta/Elev= 30
       0 1240.66     9.9 1239.37    29.8 1234.69    39.8  1231.9    69.6 1219.99
    79.5 1217.38    89.5 1216.14   139.2 1216.58   159.1 1215.76     179 1217.51
   198.9 1217.83   208.8 1217.19   222.41215.122   228.7 1214.03   239.41214.303
   248.6 1214.15   258.5 1213.14   278.4 1215.36   318.2 1214.36   328.1 1215.04
   338.1 1218.39     348 1223.25     358 1229.11   377.8 1244.55   387.8 1249.59
   397.7 1253.06   417.6 1257.15   447.4 1260.92   477.3 1262.64   487.2  1263.8
#Mann= 3 , 0 , 0
       0      .1       0   222.4    .045       0   239.4      .1       0
#XS Ineff= 2 , 0
          194.42 1217.82
Permanent Ineff=
       F       F
Bank Sta=222.4,239.4
XS Rating Curve= 0 ,0
Exp/Cntr=0.3,0.1

Type RM Length L Ch R = 1 ,8249.4  ,245.1,243.3,241.4
XS GIS Cut Line= 4
     1850519.849       386901.43     1850536.228      387080.425
     1850485.231      387117.938     1850450.825      387333.123
#Sta/Elev= 30
       0 1246.04      10 1243.24      20 1241.43      30 1240.34    39.9 1238.12
    49.9 1236.49    69.9 1234.77    79.9  1231.7    89.9 1227.11   109.8 1215.48
   119.8 1211.27   129.8 1209.85   159.8 1209.43   169.8 1209.71   179.7 1211.41
   188.8 1212.32   206.9  1212.9   215.9 1212.64     243 1210.67     253 1210.41
   262.9 1209.36   282.7 1205.36   298.1  1203.2   302.5 1202.75   313.1 1203.04
   322.3 1204.45   342.1 1210.83   361.9 1219.48   401.5 1232.97     461 1249.74
#Mann= 3 , 0 , 0
       0      .1       0   298.1    .045       0   313.1      .1       0
Bank Sta=298.1,313.1
XS Rating Curve= 0 ,0
Exp/Cntr=0.3,0.1

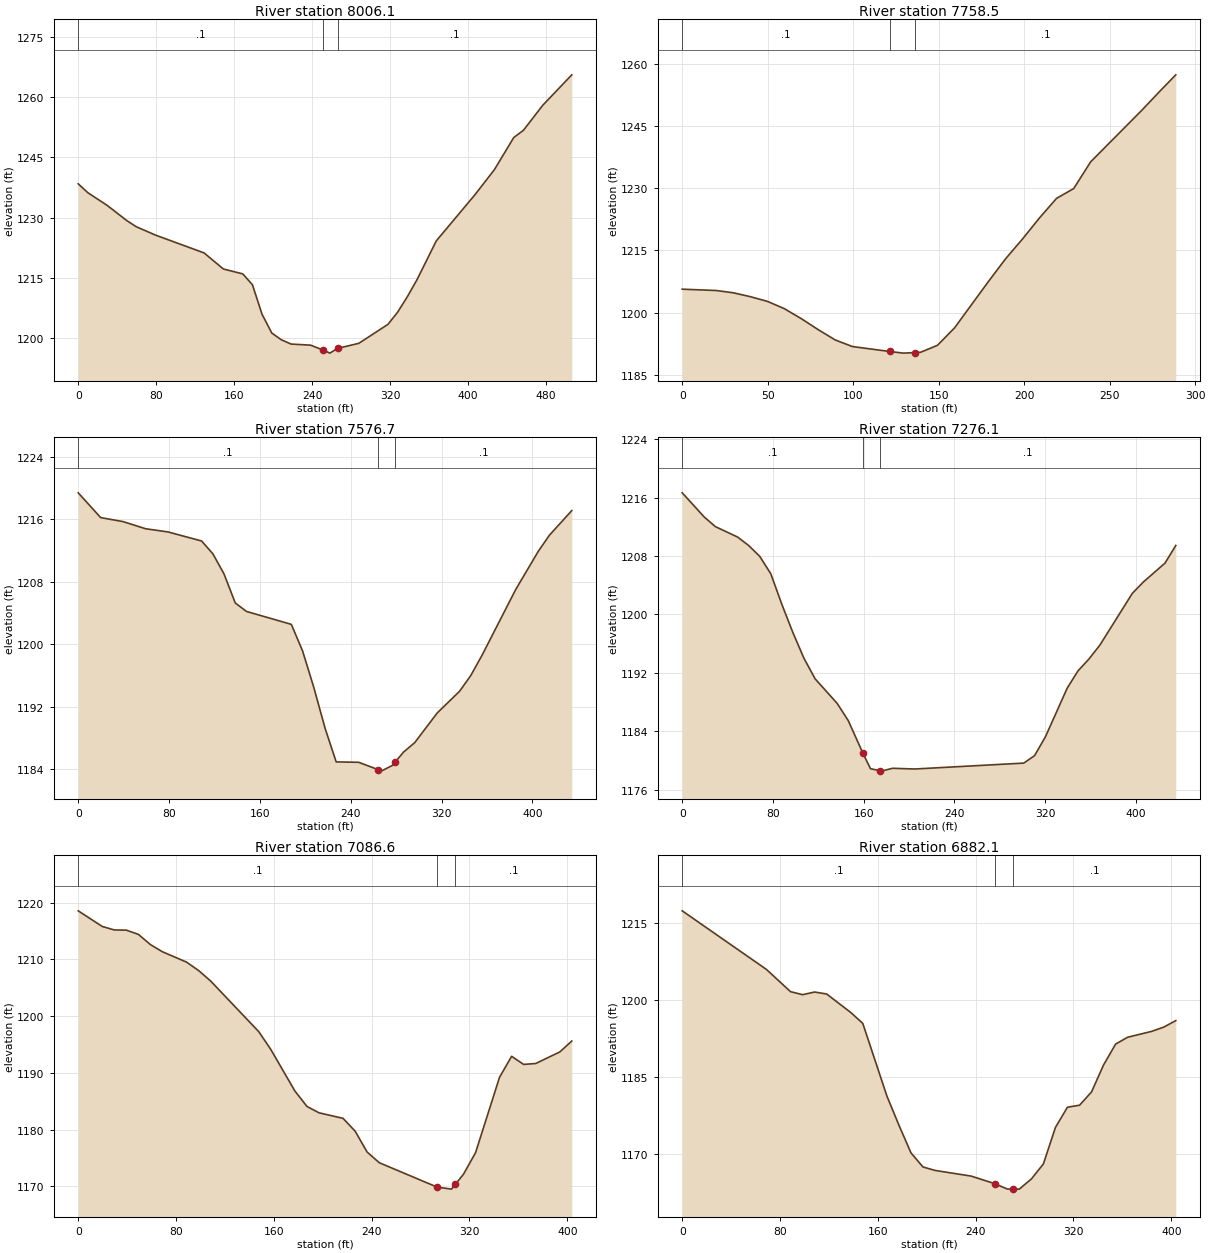
Type RM Length L Ch R = 1 ,8006.1  ,242.5,247.6,252.7
XS GIS Cut Line= 2
      1850276.52      386847.668     1850219.596       387350.78
#Sta/Elev= 30
       0 1238.41     9.9 1236.19    29.8 1233.02    49.6 1229.28    59.6  1227.7
    79.4 1225.61   129.1 1221.18   148.9 1217.17   168.8 1215.95   178.7 1213.25
   188.6 1205.86   198.6 1201.19   208.5  1199.5   218.4 1198.45   238.3 1198.18
   251.2 1196.96   258.1 1196.19   266.2 1197.38   287.9 1198.64   317.7 1203.36
   327.6 1206.38   337.6 1210.25   347.5 1214.49   367.3 1224.18     407  1235.7
   426.9 1241.94   446.8 1249.96   456.7 1251.76   476.5 1257.99   506.3 1265.59
#Mann= 3 , 0 , 0
       0      .1       0   251.2    .045       0   266.2      .1       0
Bank Sta=251.2,266.2
XS Rating Curve= 0 ,0
Exp/Cntr=0.3,0.1

Type RM Length L Ch R = 1 ,7758.5  ,164.8,181.8,198.3
XS GIS Cut Line= 2
     1850044.558      387019.543       1850012.1      387306.436
#Sta/Elev= 26
       0 1205.67    19.9 1205.35    29.9  1204.8    39.8 1203.87    49.8 1202.74
    59.7 1200.99    69.7 1198.56    79.6 1195.91    89.6 1193.42    99.6 1191.85
   121.3 1190.67   129.4 1190.27   136.3 1190.41   139.4 1190.47   149.3 1192.15
   159.3 1196.35   179.2 1207.56   189.2 1213.01   199.1 1217.78   209.1 1222.89
     219 1227.55     229  1229.9   238.9 1236.33   268.8 1248.74   278.8 1253.09
   288.7 1257.29
#Mann= 3 , 0 , 0
       0      .1       0   121.3    .045       0   136.3      .1       0
Bank Sta=121.3,136.3
XS Rating Curve= 0 ,0
Exp/Cntr=0.3,0.1

Type RM Length L Ch R = 1 ,7576.7  ,331.8,300.7,269
XS GIS Cut Line= 2
     1850142.424      386904.646     1849786.894      387154.784
#Sta/Elev= 30
       0 1219.36    19.8 1216.19    39.5 1215.68    59.3 1214.77      79 1214.36
   108.7  1213.2   118.6 1211.56   128.4 1208.99   138.3 1205.28   148.2 1204.19
   187.7 1202.54   197.6 1199.14   207.5 1194.47   217.4 1189.26   227.2 1184.95
     247  1184.9   264.2 1183.96   266.8 1183.77   276.6 1184.49   279.2 1184.94
   286.5  1186.2   296.4 1187.42   316.2 1191.21   335.9 1193.99   345.8 1196.01
   355.7  1198.6   385.3 1206.99   405.1 1211.86     415 1213.94   434.7 1217.09
#Mann= 3 , 0 , 0
       0      .1       0   264.2    .045       0   279.2      .1       0
Bank Sta=264.2,279.2
XS Rating Curve= 0 ,0
Exp/Cntr=0.3,0.1

Type RM Length L Ch R = 1 ,7276.1  ,180,189.4,198.9
XS GIS Cut Line= 3
     1849689.902      386714.305     1849768.027      386924.809
      1849730.05      387132.057
#Sta/Elev= 30
       0 1216.64    19.5 1213.32    29.3 1212.01    48.8 1210.59    58.6 1209.43
    68.3 1207.96    78.1 1205.57    87.9 1201.36    97.6 1197.51   107.4 1193.98
   117.2 1191.18   136.7 1187.81   146.4 1185.47   159.4 1180.98     166 1178.89
   174.4  1178.6   175.7 1178.55   185.5 1178.94     205 1178.84   301.2 1179.65
   310.7 1180.67   320.3 1183.26   339.5 1189.92     349 1192.27   358.6 1193.89
   368.2 1195.78   396.9 1202.88   406.5 1204.42   425.7 1207.02   435.2 1209.43
#Mann= 3 , 0 , 0
       0      .1       0   159.4    .045       0   174.4      .1       0
Bank Sta=159.4,174.4
XS Rating Curve= 0 ,0
Exp/Cntr=0.3,0.1

Type RM Length L Ch R = 1 ,7086.6  ,204.8,204.5,204.2
XS GIS Cut Line= 2
     1849632.425        386662.1     1849615.881       387065.49
#Sta/Elev= 30
       0 1218.57    19.7 1215.81    29.5  1215.2    39.4 1215.16    49.2 1214.42
    59.1 1212.61    68.9 1211.35    88.6 1209.53    98.5 1208.04   108.3  1206.2
   147.7 1197.26   157.6  1194.1   177.2 1186.81   187.1 1184.08   196.9 1182.96
   216.6 1181.98   226.5 1179.72   236.3 1176.04   246.2 1174.16   293.5 1169.86
   305.3  1169.5   308.5 1170.36   315.1 1172.12     325 1175.93   344.6 1189.22
   354.5 1192.92   364.3 1191.49   374.2 1191.65   393.9 1193.69   403.7 1195.61
#Mann= 3 , 0 , 0
       0      .1       0   293.5    .045       0   308.5      .1       0
Bank Sta=293.5,308.5
XS Rating Curve= 0 ,0
Exp/Cntr=0.3,0.1

Type RM Length L Ch R = 1 ,6882.1  ,180.9,165.1,148.7
XS GIS Cut Line= 2
     1849436.169      386665.511     1849419.625      387068.901
#Sta/Elev= 30
       0 1217.39    68.9 1205.98    88.6 1201.65    98.5 1201.06   108.3 1201.58
   118.2 1201.19   137.9 1197.59   147.7 1195.47   167.4 1181.34   177.2 1175.69
   187.1 1170.27   196.9 1167.52   206.8 1166.84   236.3 1165.74   255.6 1164.27
   265.9 1163.22   270.6 1163.21   275.7  1163.2   285.6 1165.18   295.4  1168.1
   305.3 1175.22   315.1 1179.15     325 1179.54   334.8 1182.12   344.6 1187.36
   354.5 1191.44   364.3 1192.77     384 1193.92   393.9 1194.75   403.7 1196.01
#Mann= 3 , 0 , 0
       0      .1       0   255.6    .045       0   270.6      .1       0
Bank Sta=255.6,270.6
XS Rating Curve= 0 ,0
Exp/Cntr=0.3,0.1

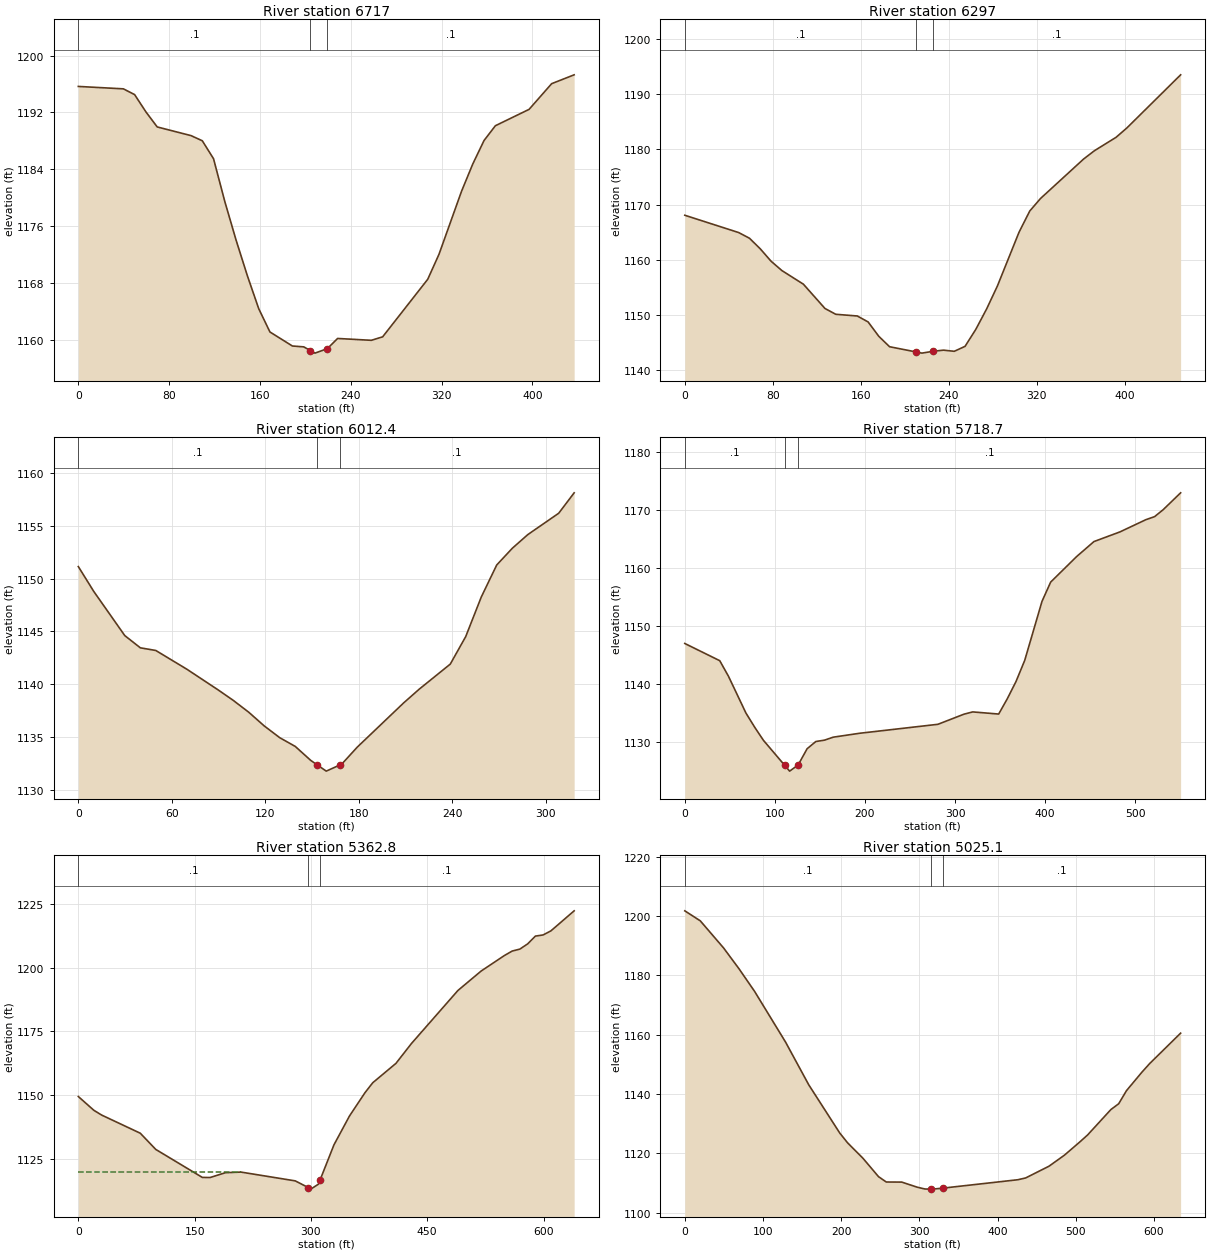
Type RM Length L Ch R = 1 ,6717    ,420.1,420.1,420.3
XS GIS Cut Line= 2
     1849141.747      386747.962     1849390.426      387107.129
#Sta/Elev= 30
       0 1195.66    39.7 1195.32    49.6 1194.51    59.6 1192.07    69.5 1189.97
    99.3 1188.75   109.2 1188.03   119.1 1185.51   129.1 1179.46     139 1174.06
   148.9 1169.08   158.9 1164.45   168.8 1161.17   188.6  1159.2   198.6 1159.08
   204.4 1158.56   208.5  1158.2   219.4 1158.83   228.4 1160.26   258.1    1160
   268.1 1160.49   307.8 1168.57   317.7 1172.07   337.6 1180.94   347.5 1184.77
   357.4 1188.06   367.4 1190.14   397.1 1192.44     417 1196.05   436.8 1197.29
#Mann= 3 , 0 , 0
       0      .1       0   204.4    .045       0   219.4      .1       0
Bank Sta=204.4,219.4
XS Rating Curve= 0 ,0
Exp/Cntr=0.3,0.1

Type RM Length L Ch R = 1 ,6297    ,286.6,284.5,281.4
XS GIS Cut Line= 2
      1848856.49      387040.306     1849113.023      387410.817
#Sta/Elev= 30
       0 1168.06      49 1164.92    58.8 1163.89    68.6 1161.97    78.4 1159.73
    88.2 1158.04   107.8 1155.56   127.4 1151.16   137.2 1150.11   156.8  1149.8
   166.6 1148.72   176.3 1146.12   186.1 1144.23   210.5 1143.27   215.5 1143.07
   225.5  1143.4   235.1 1143.61   244.9  1143.4   254.7  1144.3   264.5 1147.39
   274.3 1151.08   284.1 1155.24   303.7 1164.96   313.5 1168.83   323.3  1171.1
   362.5 1178.26   372.3 1179.76   391.9 1182.18   401.7 1183.87   450.6 1193.51
#Mann= 3 , 0 , 0
       0      .1       0   210.5    .045       0   225.5      .1       0
Bank Sta=210.5,225.5
XS Rating Curve= 0 ,0
Exp/Cntr=0.3,0.1

Type RM Length L Ch R = 1 ,6012.4  ,293.7,293.8,294.8
XS GIS Cut Line= 2
     1848686.723      387284.519     1848886.478      387532.255
#Sta/Elev= 28
       0 1151.14     9.9 1148.79    29.8 1144.61    39.8 1143.45    49.7  1143.2
    69.6 1141.43    89.5 1139.49    99.4 1138.48   109.4 1137.35   119.3 1136.06
   129.3 1134.94   139.2 1134.12   149.2 1132.79   153.1 1132.39   159.1 1131.78
   168.1 1132.38   169.1 1132.45     179 1134.05   208.8 1138.24   218.8 1139.54
   238.7 1141.91   248.6 1144.51   258.6 1148.26   268.5 1151.29   278.5 1152.87
   288.4 1154.16   308.3 1156.19   318.2 1158.12
#Mann= 3 , 0 , 0
       0      .1       0   153.1    .045       0   168.1      .1       0
Bank Sta=153.1,168.1
XS Rating Curve= 0 ,0
Exp/Cntr=0.3,0.1

Type RM Length L Ch R = 1 ,5718.7  ,347.1,355.9,360
XS GIS Cut Line= 4
     1848473.283      387490.589     1848573.978      387608.644
     1848737.172      387587.811     1848900.367      387751.005
#Sta/Elev= 30
       0 1146.96    38.8 1143.99    48.5  1141.3    67.9 1134.95    77.6 1132.51
    87.3 1130.25   110.8 1125.95   116.4 1124.93   125.8 1125.98   135.8 1128.79
   145.5 1130.04   155.2 1130.28   164.8 1130.79   193.9 1131.46     281 1133.01
     310 1134.76   319.7 1135.15   348.5 1134.78   358.2 1137.46   367.8 1140.42
   377.4 1144.04   396.6 1154.23   406.2 1157.55   435.1 1161.97   454.3 1164.55
   483.2 1166.22     512 1168.33   521.6 1168.85   531.2 1170.06   550.5 1172.96
#Mann= 3 , 0 , 0
       0      .1       0   110.8    .045       0   125.8      .1       0
Bank Sta=110.8,125.8
XS Rating Curve= 0 ,0
Exp/Cntr=0.3,0.1

Type RM Length L Ch R = 1 ,5362.8  ,341.5,337.7,333.7
XS GIS Cut Line= 2
     1848294.629      387515.543     1848426.919      388141.176
#Sta/Elev= 30
       0 1149.51      20 1144.13      30 1142.27    79.9 1135.15    99.9  1128.8
   159.9 1117.85   169.9  1117.8   189.8  1119.7   209.8 1119.93   279.8 1116.49
   296.8 1113.84   299.8 1113.26   309.7 1115.21   311.8 1116.85   329.7  1130.6
   349.7 1141.88   369.7 1151.01   379.7  1154.9   409.7 1162.51   429.6 1170.25
   489.6 1191.04   519.6 1198.66   549.5 1204.71   559.5 1206.46   569.5 1207.24
   579.5 1209.27   589.5 1212.32   599.5 1212.78   609.5 1214.37   639.5 1222.22
#Mann= 3 , 0 , 0
       0      .1       0   296.8    .045       0   311.8      .1       0
#XS Ineff= 2 , 0
          209.57    1120
Permanent Ineff=
       F       F
Bank Sta=296.8,311.8
XS Rating Curve= 0 ,0
Exp/Cntr=0.3,0.1

Type RM Length L Ch R = 1 ,5025.1  ,252.5,243.1,233.5
XS GIS Cut Line= 2
     1847930.017      387440.381     1848141.477      388038.323
#Sta/Elev= 30
       0 1201.77    19.8  1198.4    49.6 1189.26    69.4 1182.22    89.2 1174.65
   128.8 1157.57   158.6 1143.11   198.2 1126.88   208.1 1123.61   227.9 1118.37
   247.8 1112.17   257.7 1110.37   277.5 1110.34   297.3 1108.62   307.2 1108.01
   314.9 1107.98   317.1 1107.97   329.9  1108.3   426.1 1111.14     436 1111.74
   465.8 1115.69   485.6 1119.42   505.4  1123.9   515.3 1126.25     545 1134.79
     555 1136.75   564.9 1141.14   584.7 1147.39   594.6 1150.29   634.2 1160.54
#Mann= 3 , 0 , 0
       0      .1       0   314.9    .045       0   329.9      .1       0
Bank Sta=314.9,329.9
XS Rating Curve= 0 ,0
Exp/Cntr=0.3,0.1

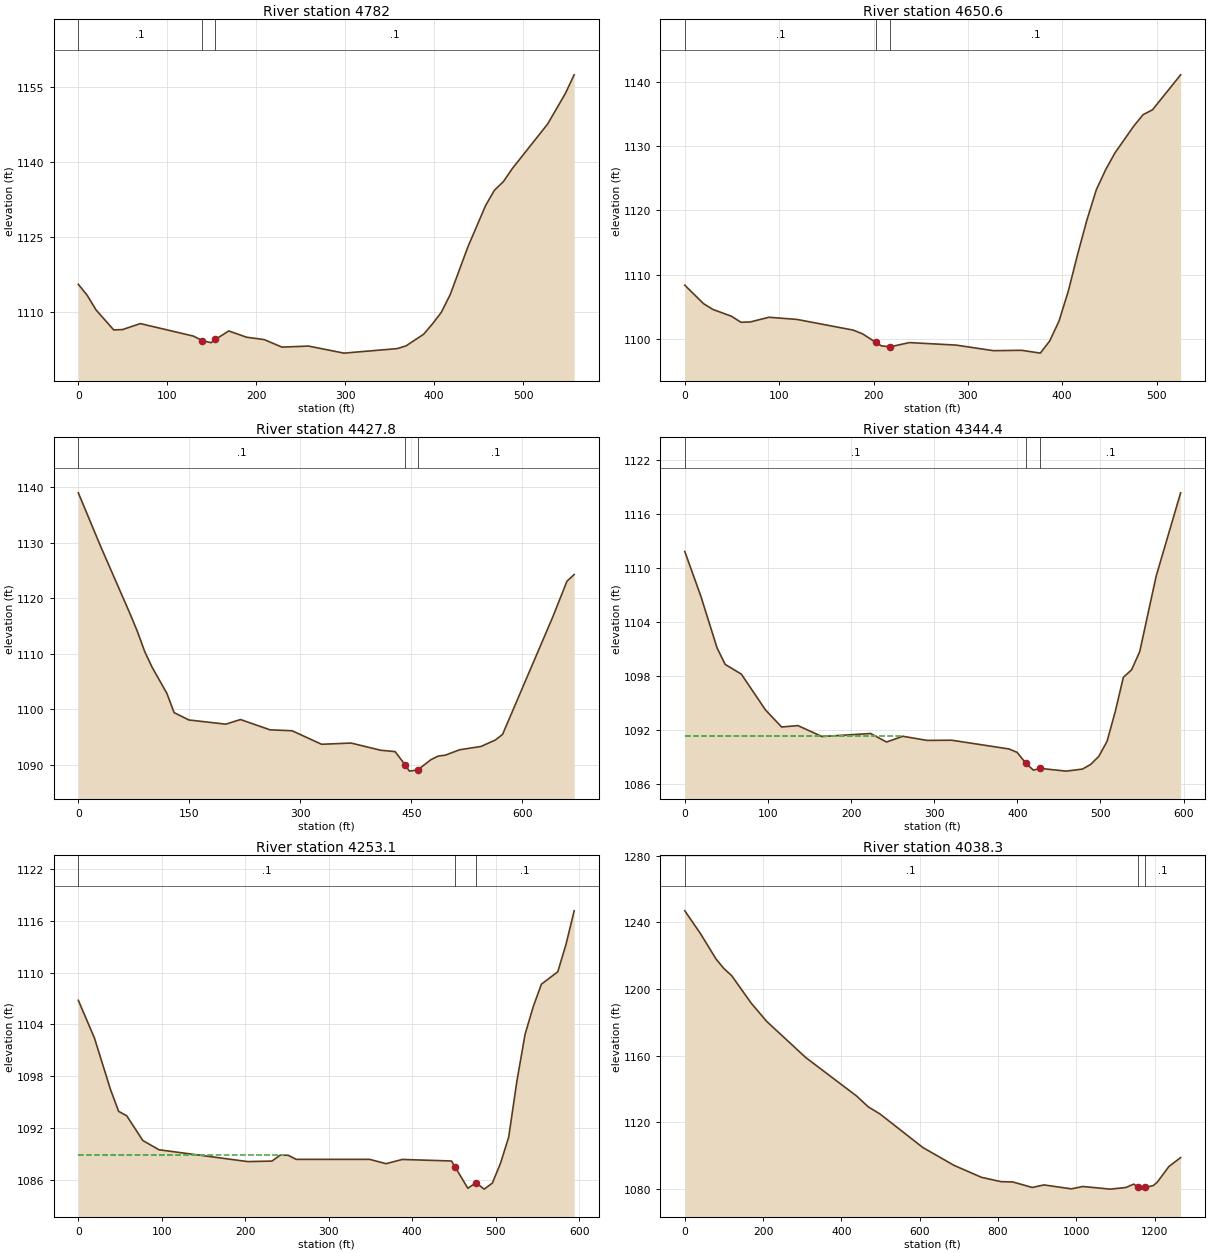
Type RM Length L Ch R = 1 ,4782    ,121.1,131.4,141.7
XS GIS Cut Line= 2
     1847699.842      387678.041     1848090.903      388075.276
#Sta/Elev= 30
       0  1115.6      10 1113.39    19.9 1110.49    39.8 1106.48    49.8 1106.56
    69.7 1107.75   129.4 1105.25   139.2 1104.37   149.3 1103.93   154.2  1104.6
   169.2 1106.28   189.1 1105.03     209 1104.55   228.9 1103.05   258.8 1103.26
   298.6 1101.85   358.4 1102.75   368.3 1103.29   388.2 1105.62   398.2 1107.71
   408.1 1110.01   418.1 1113.56     438  1123.1   457.9 1131.35   467.8 1134.39
   477.8  1136.1   487.8  1138.7   527.6 1147.62   547.5 1153.71   557.4 1157.44
#Mann= 3 , 0 , 0
       0      .1       0   139.2    .045       0   154.2      .1       0
#XS Ineff= 2 , 0
                          169.53         1106.13
Permanent Ineff=
       F       F
Bank Sta=139.2,154.2
XS Rating Curve= 0 ,0
Exp/Cntr=0.3,0.1

Type RM Length L Ch R = 1 ,4650.6  ,225.1,222.7,220.4
XS GIS Cut Line= 2
      1847636.42      387717.802     1847905.831      388168.949
#Sta/Elev= 30
       0 1108.36    19.8 1105.49    29.7 1104.59    49.6 1103.52    59.5 1102.59
    69.4 1102.64    89.2 1103.37     119 1103.03   178.5 1101.37   188.4 1100.79
   202.6 1099.45   208.2 1098.93   217.6 1098.77     238 1099.43   287.5 1099.04
   327.2 1098.17   356.9 1098.23   376.8 1097.79   386.7 1099.67   396.6 1102.77
   406.5 1107.45   416.4  1113.2   426.3 1118.56   436.2 1123.22   446.2 1126.37
   456.1 1128.98   475.9 1133.12   485.8 1134.89   495.7 1135.64   525.5 1141.08
#Mann= 3 , 0 , 0
       0      .1       0   202.6    .045       0   217.6      .1       0
Bank Sta=202.6,217.6
XS Rating Curve= 0 ,0
Exp/Cntr=0.3,0.1

Type RM Length L Ch R = 1 ,4427.8  ,74.2,83.5,103.3
XS GIS Cut Line= 3
     1847554.269      387616.866     1847593.331      388033.533
     1847697.498      388262.699
#Sta/Elev= 30
       0 1138.97    29.9 1129.42    69.8 1117.25    79.7 1114.08    89.7 1110.43
    99.6 1107.63   119.6 1102.92   129.5 1099.43   149.5 1098.11   199.3 1097.36
   219.2 1098.19   259.1 1096.34     289 1096.17   328.8 1093.74   368.7 1093.96
   408.5 1092.67   428.2 1092.42   441.81090.024   447.5 1088.91   458.81089.137
   476.6 1090.97   486.3 1091.61     496 1091.78   515.3 1092.75   544.4 1093.35
   563.7 1094.51   573.4 1095.51   641.2 1116.61   660.5 1123.08   670.2 1124.27
#Mann= 3 , 0 , 0
       0      .1       0   441.8    .045       0   458.8      .1       0
Bank Sta=441.8,458.8
XS Rating Curve= 0 ,0
Exp/Cntr=0.3,0.1

Type RM Length L Ch R = 1 ,4344.4  ,94.7,91.3,77.3
XS GIS Cut Line= 3
     1847456.513      387709.055     1847518.298       387973.85
       1847578.8      388292.745
#Sta/Elev= 30
       0 1111.83    19.4 1106.83    38.8  1101.1    48.6 1099.26      68 1098.18
    97.1 1094.19   116.5 1092.29     136 1092.45   165.1 1091.23   223.4 1091.57
   242.8 1090.62   262.2 1091.26   291.6  1090.8   321.1 1090.82   389.9 1089.85
   399.8 1089.47   410.51088.234   419.4 1087.49   427.51087.685   458.8 1087.38
   478.5 1087.61   488.3 1088.13   498.1 1089.03     508  1090.7   517.8 1093.99
   527.6 1097.82   537.5 1098.66   547.3 1100.68     567 1109.06   596.5 1118.36
#Mann= 3 , 0 , 0
       0      .1       0   410.5    .045       0   427.5      .1       0
#XS Ineff= 2 , 0
           263.6  1091.3
Permanent Ineff=
       F       F
Bank Sta=410.5,427.5
XS Rating Curve= 0 ,0
Exp/Cntr=0.3,0.1

Type RM Length L Ch R = 1 ,4253.1  ,216.3,214.8,213.3
XS GIS Cut Line= 3
     1847388.018      387728.979     1847449.519      387992.554
     1847509.787      388310.219
#Sta/Elev= 30
       0 1106.79    19.3 1102.42    38.7 1096.41    48.3 1093.92      58 1093.41
    77.3 1090.54    96.7 1089.47     203  1088.1     232 1088.16   241.7 1088.84
   251.3 1088.84     261 1088.36     349 1088.36   368.6 1087.86   388.2 1088.35
     447 1088.17   451.31087.497   466.6 1085.01   476.4 1085.65   486.2 1084.91
     496 1085.61   505.8 1087.91   515.6 1090.95   525.4 1097.43   535.2 1102.85
     545 1106.06   554.8 1108.66   574.4  1110.1   584.2 1113.26     594 1117.16
#Mann= 3 , 0 , 0
       0      .1       0   451.3    .045       0   476.4      .1       0
#XS Ineff= 2 , 0
          246.06 1088.92
Permanent Ineff=
       F       F
Bank Sta=451.3,476.4
XS Rating Curve= 0 ,0
Exp/Cntr=0.3,0.1

Type RM Length L Ch R = 1 ,4038.3  ,211.2,190.7,170.1
XS GIS Cut Line= 2
     1846987.531      387080.662     1847298.355      388308.599
#Sta/Elev= 30
       0 1246.88    39.9 1233.28    79.8 1217.99    99.7 1212.32   119.7 1208.02
   169.6 1191.53   209.4 1180.52   309.2 1158.87   438.8 1135.83   468.8 1129.31
   498.7 1125.05   608.4 1104.89   688.2 1094.19     758 1087.05   807.9 1084.46
   837.8 1084.29   887.7 1080.98   917.6  1082.5   987.4 1080.15  1017.3 1081.55
  1087.1 1079.98    1127 1080.97    1147    1083    1157 1081.35  1166.9 1080.07
  1176.9 1081.04  1196.8 1082.11  1206.8 1084.09  1236.7 1093.52  1266.7 1098.91
#Mann= 3 , 0 , 0
       0      .1       0    1157    .045       0  1176.9      .1       0
#XS Ineff= 2 , 0
         1145.79 1082.85
Permanent Ineff=
       F       F
Bank Sta=1157,1176.9
XS Rating Curve= 0 ,0
Exp/Cntr=0.3,0.1

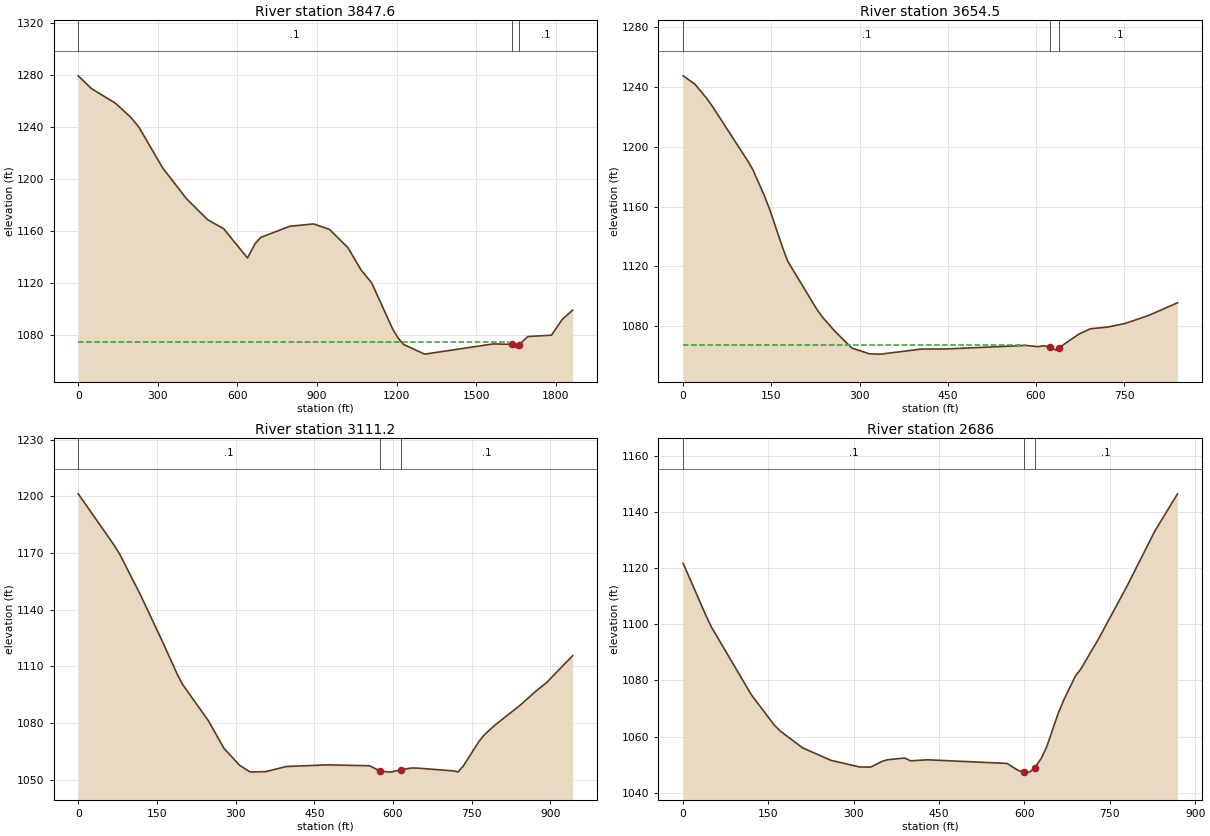
Type RM Length L Ch R = 1 ,3847.6  ,198.5,193.1,187.5
XS GIS Cut Line= 2
     1845590.974      387559.258     1847291.873      388320.264
#Sta/Elev= 30
       0 1279.51    49.8 1269.65   139.5 1258.52   199.3 1247.34   229.2 1239.78
   318.9 1208.39   408.6 1184.76   488.3 1168.63     548 1161.85   637.7 1139.31
   667.6 1150.57   687.6 1155.07   797.2 1163.68   886.8  1165.5   946.6 1161.34
  1016.4 1147.24  1066.2 1130.03  1106.1 1120.06  1185.8  1084.3  1205.7 1077.62
  1225.6 1072.79  1305.4 1065.26  1564.4 1073.12  1634.2 1072.76  1654.1 1070.11
  1660.5 1072.27    1694  1078.8  1783.7 1079.85  1823.5 1091.84  1863.4 1099.15
#Mann= 3 , 0 , 0
       0      .1       0  1634.2    .045       0  1660.5      .1       0
#XS Ineff= 2 , 0
         1619.13 1074.53
Permanent Ineff=
       F       F
Bank Sta=1634.2,1660.5
XS Rating Curve= 0 ,0
Exp/Cntr=0.3,0.1

Type RM Length L Ch R = 1 ,3654.5  ,539.2,543.2,528.4
XS GIS Cut Line= 2
      1846384.14      388290.599      1847211.55      388440.101
#Sta/Elev= 30
       0 1247.55    19.8 1242.04    39.6 1232.68    49.5 1227.26   108.8 1191.25
   118.7 1184.61   138.5 1166.96   148.4 1156.81   168.2 1133.57     178 1123.31
   227.5 1091.12   237.4 1085.75   257.2 1076.86   286.9 1065.26   316.5 1061.42
   336.3 1061.19   405.6 1064.61   445.1 1064.63   583.6 1067.01   603.4 1066.19
   613.3 1066.78   624.7  1065.9   633.1 1063.97   639.7 1065.59   672.6 1074.48
   692.4 1078.16   722.1 1079.31   751.8 1081.75   791.4 1087.04   840.8  1095.6
#Mann= 3 , 0 , 0
       0      .1       0   624.7    .045       0   639.7      .1       0
#XS Ineff= 2 , 0
           583.7  1067.2
Permanent Ineff=
       F       F
Bank Sta=624.7,639.7
XS Rating Curve= 0 ,0
Exp/Cntr=0.3,0.1

Type RM Length L Ch R = 1 ,3111.2  ,425,425.2,423.9
XS GIS Cut Line= 2
     1846301.385      388759.499     1847242.023      388818.826
#Sta/Elev= 30
       0  1201.3    69.4 1173.74    79.4 1169.19     119 1147.65   158.7 1124.26
   188.5 1106.05   198.4 1100.71     248 1081.34   277.8 1066.72   307.6 1057.74
   327.4 1054.22   357.2 1054.37   396.8 1057.11   476.2 1057.98   555.6 1057.49
   575.4 1054.69   595.3 1054.13   615.1 1055.39     635 1056.31   644.9 1056.29
   714.3  1054.8   724.2 1054.24   734.2 1057.41   763.9 1070.37   773.8 1073.75
   793.7 1078.83   843.3 1089.73   873.1 1097.11   892.9  1101.5   942.5 1115.73
#Mann= 3 , 0 , 0
       0      .1       0   575.4    .045       0   615.1      .1       0
#XS Ineff= 2 , 0
           515.5 1057.66
Permanent Ineff=
       F       F
Bank Sta=575.4,615.1
XS Rating Curve= 0 ,0
Exp/Cntr=0.3,0.1

Type RM Length L Ch R = 1 ,2686    ,2667.5,2686,2703.8
XS GIS Cut Line= 2
     1846406.231      389122.555     1847272.585        389190.7
#Sta/Elev= 30
       0  1121.7      40 1103.15    49.9 1098.94   119.9  1074.9   159.8 1064.22
   169.8 1062.14   209.8 1056.03   259.7 1051.56   309.6 1049.22   329.6 1049.14
   349.6 1051.19   359.6 1051.77   389.6 1052.39   399.6 1051.38   429.5 1051.75
   569.4 1050.46   589.3 1047.91   599.3 1047.36   609.3 1047.38   617.9  1048.9
   629.3 1052.18   639.3 1056.52   659.3  1068.3   669.2 1073.08   689.2 1081.45
   699.2 1084.11   729.2 1094.43   779.1 1113.11   829.1 1133.15     869 1146.42
#Mann= 3 , 0 , 0
       0      .1       0   599.3    .045       0   617.9      .1       0
#XS Ineff= 2 , 0
          390.61 1052.26
Permanent Ineff=
       F       F
Bank Sta=599.3,617.9
XS Rating Curve= 0 ,0
Exp/Cntr=0.3,0.1

Chan Stop Cuts=-1
Use User Specified Reach Order=0
Composite Channel Slope=5